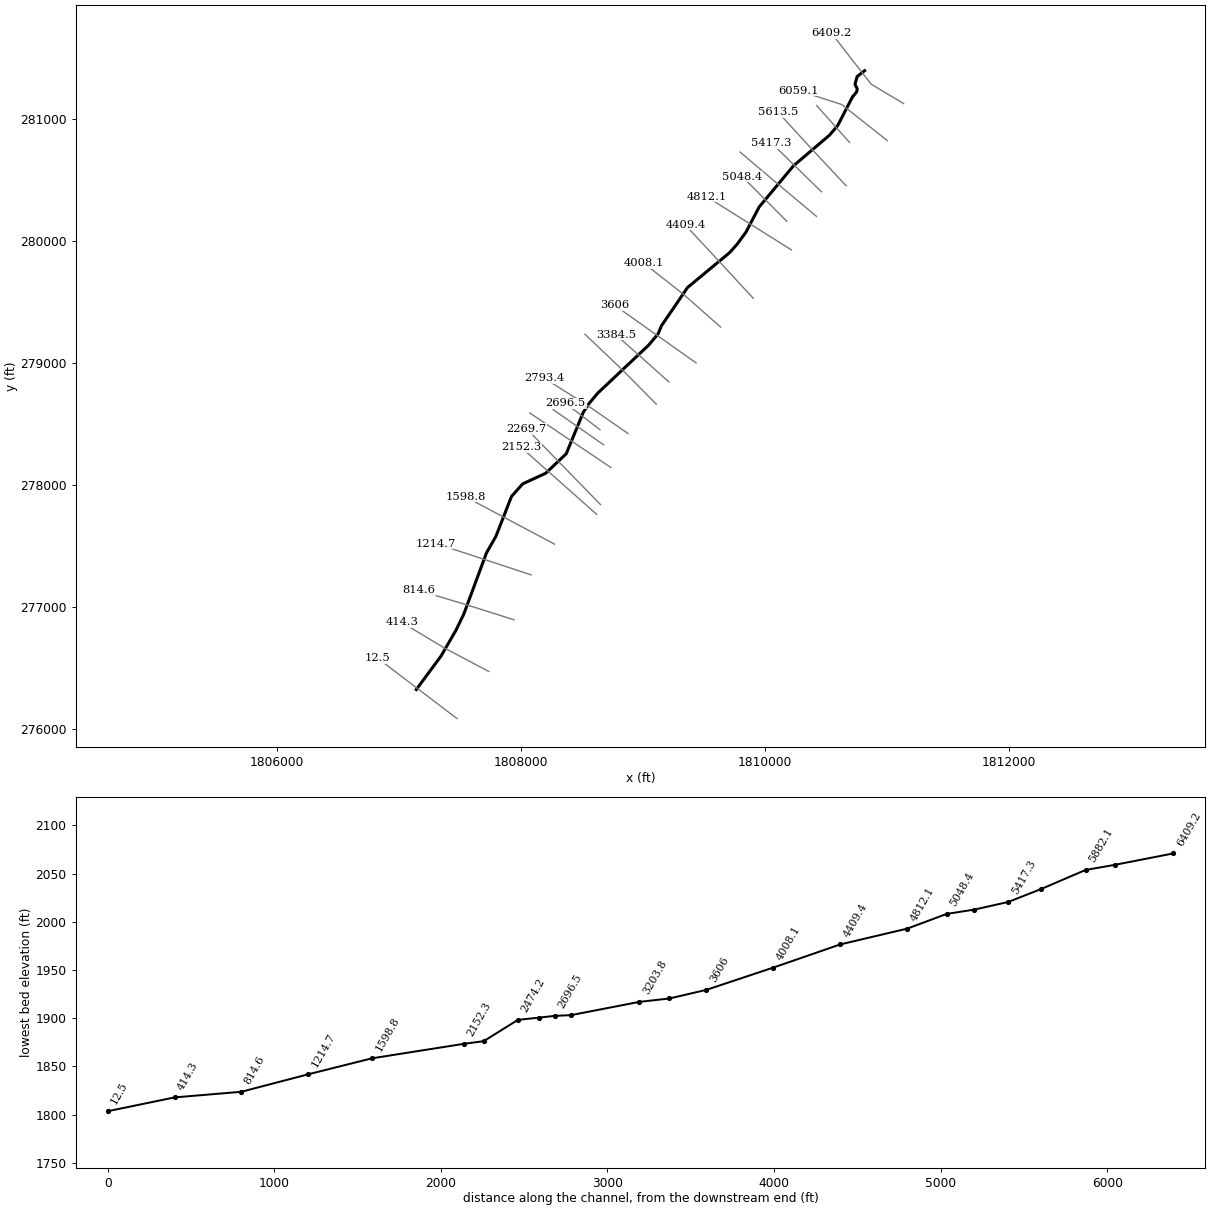
--- ToneyFk2.prj (project) ---

Proj Title=ToneyFk2
Current Plan=p01
Default Exp/Contr=0,0
English Units
Geom File=g01
Flow File=f01
Plan File=p01
BEGIN DESCRIPTION:
END DESCRIPTION:
DSS Export Rating Curves= 0
DSS Export Rating Curve Sorted= 0
DSS Export Volume Flow Curves= 0
DXF OffsetX= 0
DXF OffsetY= 0
DXF ScaleX= 0
DXF ScaleY= 0

--- ToneyFk2.p01 (plan) ---

Plan Title=Floodplain
Program Version=4.00
Geom File=g01
Flow File=f01
K Sum by GR=0
Std Step Tol=0.01
Critical Tol=0.01
Num of Std Step Trials=20
Max Error Tol=0.3
Flow Tol Ratio=0.001
Split Flow NTrial=30
Split Flow Tol=0.02
Split Flow Ratio=0.02
Log Output Level=0
Friction Slope Method=1
Unsteady Friction Slope Method=2
Unsteady Bridges Friction Slope Method=1
Global Log Level=0
CheckData=False
Run HTab=0
Run UNet=0
Run PostProcess=0
UNET Theta=0
UNET Theta Warmup=0
UNET ZTol=0
UNET ZSATol=0
UNET MxIter=0
UNET MaxInSteps=0
UNET DtIC=0
UNET DtMin=0
UNET MaxCRTS=0
UNET WFStab=0
UNET SFStab=0
UNET WFX=0
UNET SFX=0
UNET DSS MLevel=0
UNET DZMax Abort=0
UNET Convert EG Bridges=0
UNET Use Existing IB Tables=0
UNET Froude Limit=0
UNET Froude Power=0
Write IC File=0
Echo Input=False
Echo Output=False
Write Detailed=0

--- ToneyFk2.f01 (steady flow) ---

Flow Title=NFF Regression Equation
Program Version=4.00
Number of Profiles=1
Profile Names=P100yr
River Rch & RM=ToneyFk2,Main      ,6409.2
336.1701
River Rch & RM=ToneyFk2,Main      ,6409.2
530.3787
River Rch & RM=ToneyFk2,Main      ,6059.1
344.2818
River Rch & RM=ToneyFk2,Main      ,6059.1
542.6274
River Rch & RM=ToneyFk2,Main      ,5882.1
630.7177
River Rch & RM=ToneyFk2,Main      ,5882.1
409.6379
River Rch & RM=ToneyFk2,Main      ,4008.1
662.4780
River Rch & RM=ToneyFk2,Main      ,4008.1
434.8096
River Rch & RM=ToneyFk2,Main      ,3606
832.7255
River Rch & RM=ToneyFk2,Main      ,3606
565.7604
River Rch & RM=ToneyFk2,Main      ,2601.2
866.3030
River Rch & RM=ToneyFk2,Main      ,2601.2
592.9580
River Rch & RM=ToneyFk2,Main      ,1214.7
933.6540
River Rch & RM=ToneyFk2,Main      ,1214.7
646.1591
River Rch & RM=ToneyFk2,Main      ,12.5
1009.973
River Rch & RM=ToneyFk2,Main      ,12.5
708.5709
Boundary for River Rch & Prof#=ToneyFk2,Main      ,1
Up Type=0
Dn Type=3
Dn Slope=0.030846

--- ToneyFk2.g01 (geometry) ---

Geom Title=USGS 10m DEM
Program Version=4.00

River Reach=ToneyFk2        ,Main
Reach XY= 30
     1810817.064      281395.617     1810755.787      281347.428
     1810738.534      281284.367     1810756.977      281246.292
     1810752.217        281221.9     1810716.522      281178.471
     1810597.372      280946.955     1810529.717      280867.327
     1810234.647      280616.337     1809952.624      280278.344
     1809844.964      280072.514     1809772.384      279973.162
     1809710.512      279904.152     1809366.053       279618.59
     1809152.647       279305.62      1809125.11      279239.031
     1809047.176      279146.223     1808630.035      278753.046
     1808557.058      278665.791     1808511.844      278595.987
     1808372.236      278256.485     1808203.279      278096.253
     1808015.284      278009.792     1807923.361      277906.314
     1807796.353      277580.656     1807718.617      277444.221
     1807532.434      276941.796     1807467.164      276808.052
     1807346.593      276599.434      1807143.37      276324.416

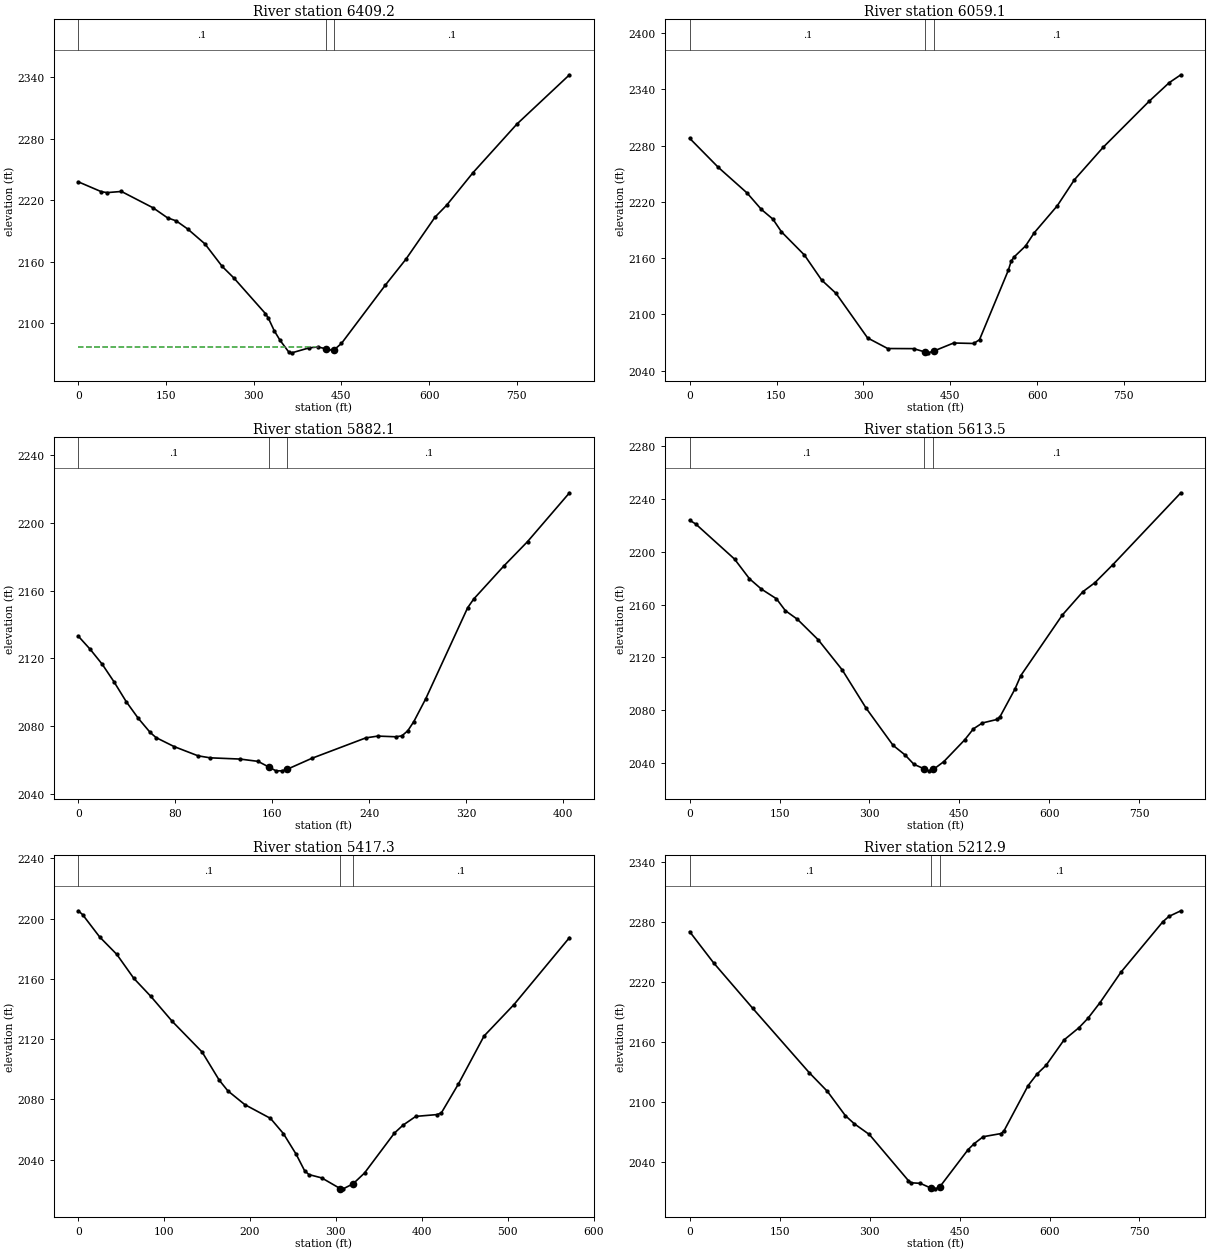
Type RM Length L Ch R = 1 ,6409.2  ,344.4,350.1,355.7
XS GIS Cut Line= 3
     1811137.219      281126.106     1810870.973      281285.098
     1810545.309      281703.081
#Sta/Elev= 30
       0 2237.94    39.4  2228.3    49.2 2227.41    73.8 2228.52     128 2212.52
   152.6 2202.77   167.4 2199.82     187 2191.92   216.6 2177.32   246.1 2155.32
   265.8  2144.2   320.1 2109.22   325.1 2104.76   335.1 2092.52   345.1 2083.12
   360.1 2071.63   365.1 2070.95   395.1 2075.85   410.1  2076.7   422.9 2074.92
   435.1 2073.27   437.9 2074.08   450.1 2080.18     525    2137     560 2162.17
     610 2203.42     630 2215.16     675 2246.88     750 2294.28     840 2342.46
#Mann= 3 , 0 , 0
       0      .1       0   422.9    .045       0   437.9      .1       0
#XS Ineff= 2 , 0
          412.75 2076.91
Permanent Ineff=
       F       F
Bank Sta=422.9,437.9
XS Rating Curve= 0 ,0
Exp/Cntr=0.3,0.1

Type RM Length L Ch R = 1 ,6059.1  ,180.9,177,173.2
XS GIS Cut Line= 3
     1811002.335      280823.361     1810629.292      281118.634
     1810274.741      281232.909
#Sta/Elev= 30
       0 2287.69    49.6 2256.67    99.1 2229.47   123.9 2211.88   143.7 2201.62
   158.6 2188.02   198.2 2163.33     228 2136.64   252.8 2122.48   307.3 2075.01
     342 2063.74   386.6 2063.61   406.4 2060.08   406.4 2060.07   411.3 2059.14
   421.4 2060.98   455.9 2069.62   490.7 2069.11   500.6  2073.2   550.3 2147.05
   555.2 2156.67   560.2 2161.21   580.1    2173     595 2186.98   634.7 2215.66
   664.5 2243.56   714.2 2278.15   793.6 2327.19   828.4 2347.04   848.3 2355.35
#Mann= 3 , 0 , 0
       0      .1       0   406.4    .045       0   421.4      .1       0
Bank Sta=406.4,421.4
XS Rating Curve= 0 ,0
Exp/Cntr=0.3,0.1

Type RM Length L Ch R = 1 ,5882.1  ,268.1,268.6,269
XS GIS Cut Line= 2
     1810693.822      280807.695     1810424.191      281110.208
#Sta/Elev= 30
       0 2133.13     9.9 2125.32    19.8 2116.53    29.6 2106.08    39.5 2094.59
    49.4 2084.79    59.3  2076.4    64.2 2073.35    79.1 2068.06    98.8 2062.63
   108.7 2061.45   133.4 2060.72   148.3 2059.36   157.5  2055.9   163.1 2053.79
     168 2053.78   172.5 2054.76   192.7 2061.17   237.2  2073.2   247.1 2074.25
   261.9 2073.85   266.9 2074.38   271.8 2077.38   276.8 2082.81   286.6 2096.23
   321.2 2149.88   326.2 2155.01   350.9 2174.36   370.6 2188.84   405.2  2217.6
#Mann= 3 , 0 , 0
       0      .1       0   157.5    .045       0   172.5      .1       0
Bank Sta=157.5,172.5
XS Rating Curve= 0 ,0
Exp/Cntr=0.3,0.1

Type RM Length L Ch R = 1 ,5613.5  ,195.1,196.1,197.3
XS GIS Cut Line= 3
     1810665.658      280452.793     1810385.878      280751.511
     1810108.734      281054.063
#Sta/Elev= 30
       0 2223.98      10  2221.2    74.9 2194.53    99.8  2179.6   119.8 2171.73
   144.8 2164.43   159.7  2155.4   179.7 2148.89   214.6 2133.26   254.6 2110.44
   294.5 2081.38   339.4 2053.23   359.4 2045.94   374.3 2038.79   391.6 2035.34
   399.3 2033.87   406.6 2034.92   424.1 2040.87   458.7 2057.27   473.5 2065.73
   488.4 2070.18   513.1 2072.89     518 2075.06   542.8 2095.94   552.6 2106.17
   621.8 2152.07   656.4 2169.88   676.2 2176.62   705.9 2190.17   819.6 2244.83
#Mann= 3 , 0 , 0
       0      .1       0   391.6    .045       0   406.6      .1       0
Bank Sta=391.6,406.6
XS Rating Curve= 0 ,0
Exp/Cntr=0.3,0.1

Type RM Length L Ch R = 1 ,5417.3  ,202.7,204.5,206.1
XS GIS Cut Line= 2
     1810463.649      280403.248      1810054.27      280802.762
#Sta/Elev= 30
       0 2205.23       5 2202.69    24.9 2187.83    44.8  2176.3    64.7 2160.32
    84.6  2148.3   109.4 2131.79   144.2 2111.42   164.1 2092.76   174.1 2085.66
     194 2076.46   223.8 2067.35   238.8 2057.28   253.7 2043.53   263.6 2032.52
   268.6 2030.02   283.5 2027.81     305 2020.71   308.4 2020.55     320 2023.89
   333.3 2031.05   368.1 2057.56     378 2062.78     393 2068.67   417.8 2069.87
   422.8    2071   442.7 2090.25   472.5 2122.05   507.4 2142.97     572 2187.43
#Mann= 3 , 0 , 0
       0      .1       0     305    .045       0     320      .1       0
Bank Sta=305,320
XS Rating Curve= 0 ,0
Exp/Cntr=0.3,0.1

Type RM Length L Ch R = 1 ,5212.9  ,166.5,164.5,162.5
XS GIS Cut Line= 3
     1810422.907      280201.784      1810108.92      280464.657
     1809796.194      280729.038
#Sta/Elev= 30
       0 2270.36      40 2239.05   104.9 2193.72   199.8 2128.77   229.7 2110.27
   259.7  2085.9   274.7 2077.75   299.6 2067.08   364.6 2020.94   369.6 2018.66
   384.5 2018.14     402 2013.43   409.5 2012.61     417 2014.55   464.4 2052.02
   474.4 2057.87   489.4 2064.85   519.4 2068.03   524.4 2071.07   564.3 2116.06
   579.3 2127.73   594.3 2136.45   624.2 2161.82   649.2 2174.16   664.2  2183.6
   684.2 2199.23   719.1 2229.73     789  2280.3     799 2285.61     819 2291.28
#Mann= 3 , 0 , 0
       0      .1       0     402    .045       0     417      .1       0
Bank Sta=402,417
XS Rating Curve= 0 ,0
Exp/Cntr=0.3,0.1

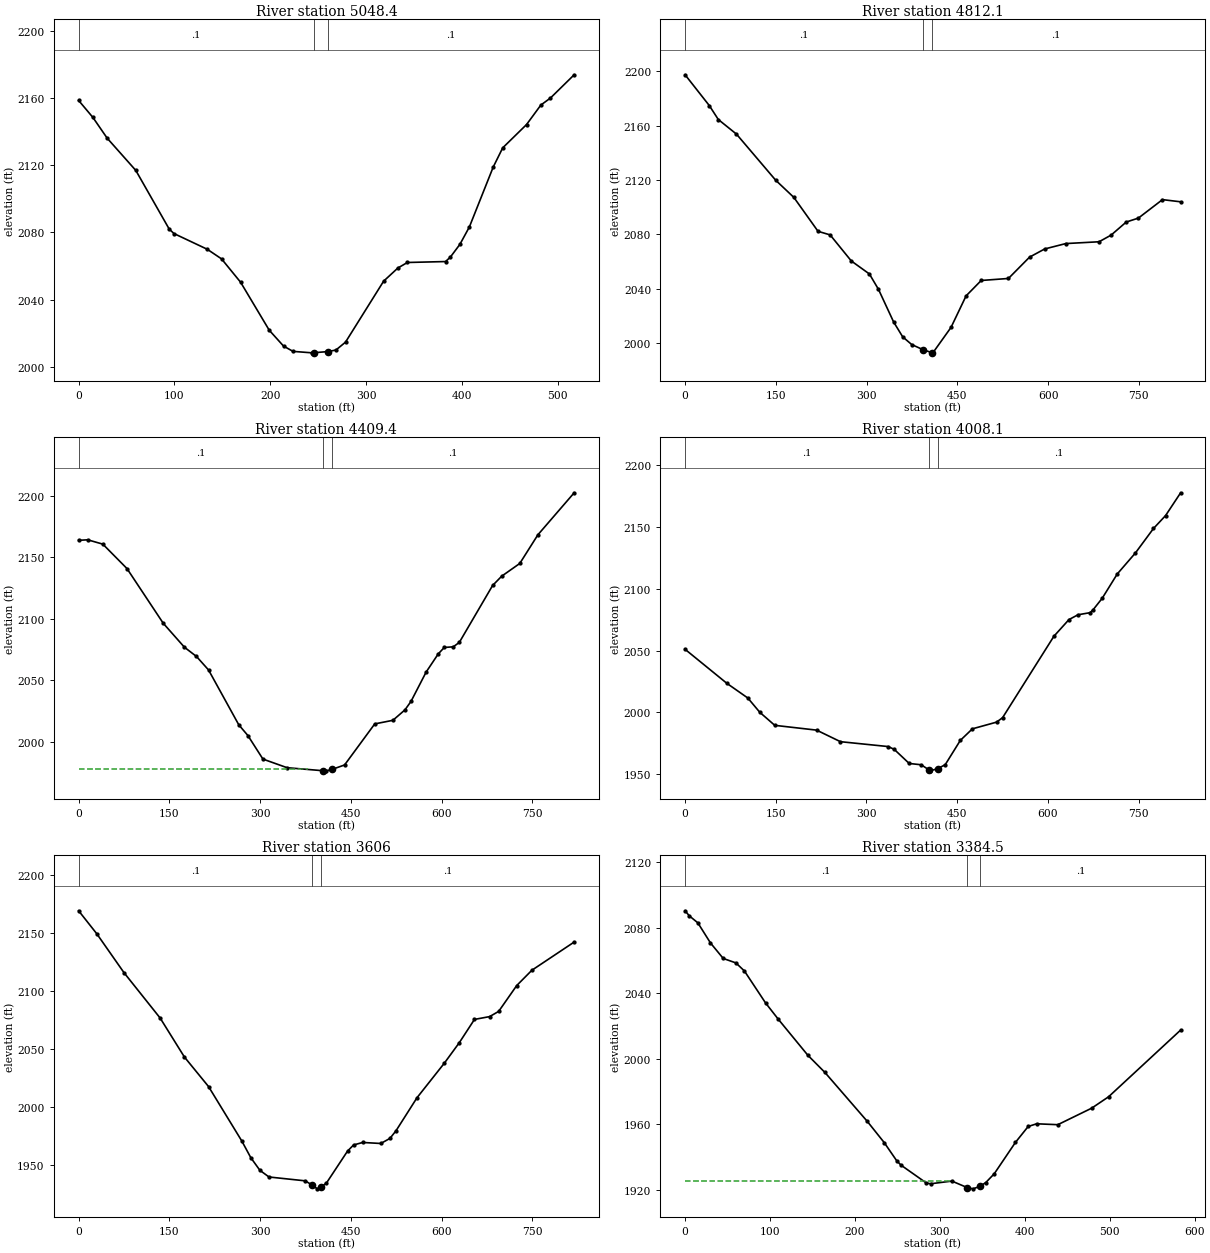
Type RM Length L Ch R = 1 ,5048.4  ,231.2,236.3,241.3
XS GIS Cut Line= 2
     1810179.221      280161.566     1809814.233      280528.199
#Sta/Elev= 30
       0  2158.8    14.9 2148.66    29.8 2136.28    59.7 2117.03    94.5 2082.09
    99.5 2079.37   134.3 2069.98   149.2 2064.25   169.1  2050.3     199 2021.66
   213.9 2012.22   223.8 2009.05   243.7 2008.18   245.4 2008.24   260.4 2008.94
   268.6 2009.86   278.6 2014.56   318.4 2050.96   333.3 2058.82   343.2  2062.1
     383 2062.66     388 2065.27     398 2072.91   407.9 2083.31   432.8 2119.07
   442.7 2130.51   467.6 2144.43   482.5 2156.04   492.5 2160.23   517.3 2174.12
#Mann= 3 , 0 , 0
       0      .1       0   245.4    .045       0   260.4      .1       0
Bank Sta=245.4,260.4
XS Rating Curve= 0 ,0
Exp/Cntr=0.3,0.1

Type RM Length L Ch R = 1 ,4812.1  ,408.7,402.7,396.8
XS GIS Cut Line= 3
     1810217.491       279927.01     1809870.722      280144.821
     1809523.954      280362.632
#Sta/Elev= 30
       0 2197.35      40 2174.71    54.9 2164.46    84.9 2153.73   149.8 2119.79
   179.8 2107.18   219.7 2082.27   239.7 2079.64   274.7 2060.47   304.6 2050.91
   319.6 2039.61   344.6 2015.65   359.6  2004.7   374.5 1999.04   392.8 1995.34
   407.8 1993.06   409.5 1992.93   439.5 2011.63   464.4 2034.81   489.4 2046.13
   534.4 2047.61   569.3 2063.29   594.3  2069.3   629.2 2073.26   684.2 2074.59
   704.1 2079.49   729.1  2089.1   749.1 2091.97     789 2105.57     819 2103.96
#Mann= 3 , 0 , 0
       0      .1       0   392.8    .045       0   407.8      .1       0
Bank Sta=392.8,407.8
XS Rating Curve= 0 ,0
Exp/Cntr=0.3,0.1

Type RM Length L Ch R = 1 ,4409.4  ,398.9,401.3,404.9
XS GIS Cut Line= 3
     1809904.647      279530.805     1809626.479      279831.325
     1809348.311      280131.846
#Sta/Elev= 30
       0 2163.96      15 2164.38      40 2160.85    79.9    2141   139.8 2096.54
   174.8 2077.05   194.8  2069.5   214.7 2058.55   264.7 2013.93   279.7 2005.23
   304.6 1986.07   344.6 1979.05   404.2 1976.59   409.5 1976.51   419.2 1977.76
   439.5 1981.27   489.4 2014.68   519.4  2017.6   539.3 2026.07   549.3 2032.95
   574.3  2056.8   594.3 2071.56   604.3 2076.84   619.2 2077.36   629.2 2080.97
   684.2 2127.24   699.2 2134.79   729.1 2145.14   759.1 2168.49     819 2202.62
#Mann= 3 , 0 , 0
       0      .1       0   404.2    .045       0   419.2      .1       0
#XS Ineff= 2 , 0
          379.38 1977.79
Permanent Ineff=
       F       F
Bank Sta=404.2,419.2
XS Rating Curve= 0 ,0
Exp/Cntr=0.3,0.1

Type RM Length L Ch R = 1 ,4008.1  ,399.7,402.1,403.3
XS GIS Cut Line= 3
     1809637.085      279295.258     1809328.997      279566.189
     1809007.032      279819.008
#Sta/Elev= 30
       0 2050.98    69.2 2023.38   103.8  2011.5   123.6 1999.93   148.3 1989.38
   217.5  1985.5     257 1976.13   336.1 1972.17     346 1969.86   370.7 1958.47
   390.5 1957.44   402.8 1953.46   405.3 1952.51   417.8  1954.3   430.2 1957.47
   455.2 1977.18   475.2 1986.56   515.1 1991.97   525.1 1995.59     610 2061.58
   634.9 2075.09   649.9 2078.99   669.9 2080.69   674.9 2083.09   689.8  2092.3
   714.8 2112.06   744.8 2129.07   774.7 2148.91   794.7 2159.38   819.6 2177.84
#Mann= 3 , 0 , 0
       0      .1       0   402.8    .045       0   417.8      .1       0
Bank Sta=402.8,417.8
XS Rating Curve= 0 ,0
Exp/Cntr=0.3,0.1

Type RM Length L Ch R = 1 ,3606    ,224.1,221.5,219
XS GIS Cut Line= 3
     1809436.937      279000.432     1809102.615      279236.903
     1808768.293      279473.375
#Sta/Elev= 30
       0 2169.19      30 2149.36    74.9 2115.86   134.8 2076.62   174.8 2043.08
   214.7 2017.59   269.7 1970.61   284.6 1956.21   299.6 1945.35   314.6 1939.59
   374.5 1936.27     386 1932.59   394.5 1929.37     401 1931.08   409.5 1934.32
   444.5 1961.97   454.4 1967.19   469.4 1969.37   499.4 1968.49   514.4 1972.83
   524.4 1979.34   559.3    2008   604.3 2037.68   629.2 2055.46   654.2 2075.49
   679.2 2077.91   694.2 2082.41   724.1 2104.74   749.1  2117.9     819 2142.22
#Mann= 3 , 0 , 0
       0      .1       0     386    .045       0     401      .1       0
Bank Sta=386,401
XS Rating Curve= 0 ,0
Exp/Cntr=0.3,0.1

Type RM Length L Ch R = 1 ,3384.5  ,182.1,180.7,179.6
XS GIS Cut Line= 2
     1809214.139      278844.649     1808778.455      279232.654
#Sta/Elev= 30
       0 2090.47       5 2087.35      15  2083.1    29.9 2070.78    44.9 2061.31
    59.8 2058.59    69.8 2053.68    94.7 2034.14   109.7 2024.15   144.6 2002.06
   164.6 1991.61   214.4 1961.74   234.4 1948.72   249.3 1937.47   254.3 1934.87
   284.2 1923.93   289.2 1923.53   314.1 1925.16   332.3 1921.16   339.1 1920.42
   347.3 1922.03     354 1924.27     364 1929.66   388.9 1948.82   403.9 1958.55
   413.9  1960.2   438.8 1959.65   478.7 1969.76   498.6 1976.73   583.4 2017.52
#Mann= 3 , 0 , 0
       0      .1       0   332.3    .045       0   347.3      .1       0
#XS Ineff= 2 , 0
          311.96 1925.46
Permanent Ineff=
       F       F
Bank Sta=332.3,347.3
XS Rating Curve= 0 ,0
Exp/Cntr=0.3,0.1

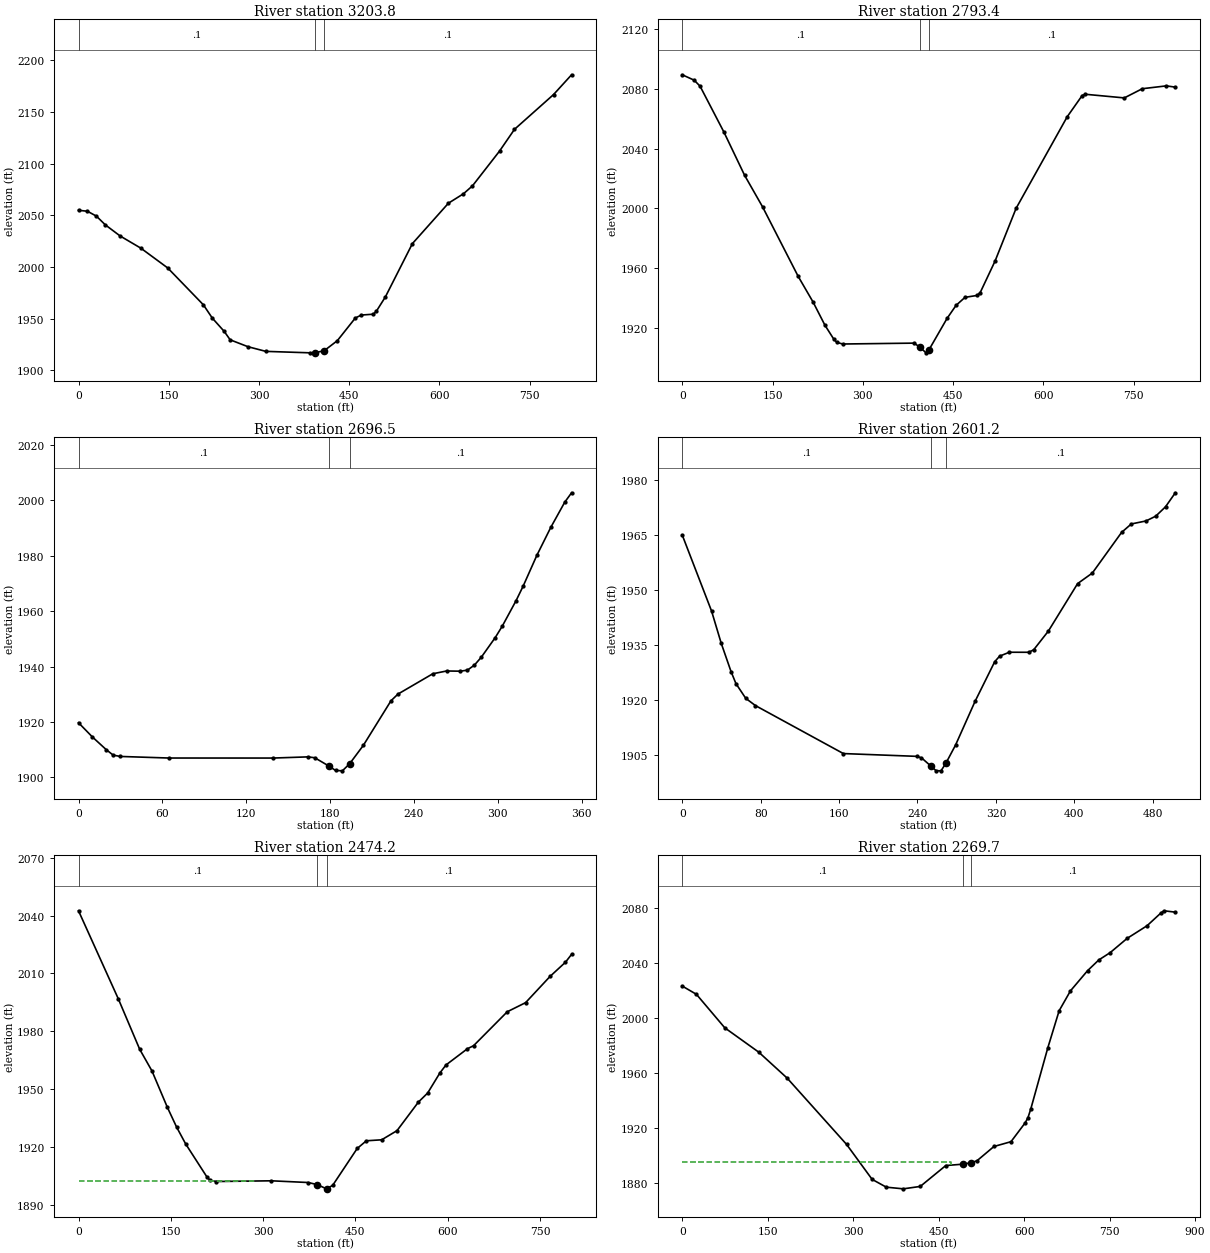
Type RM Length L Ch R = 1 ,3203.8  ,406.2,410.3,414.8
XS GIS Cut Line= 3
     1809110.586      278662.356     1808821.888      278953.863
     1808525.306      279235.907
#Sta/Elev= 30
       0  2054.8    14.8 2053.89    29.7 2049.17    44.5 2040.75    69.2 2029.95
   103.8  2018.1   148.3 1999.02   207.6 1963.34   222.4 1950.52   242.2 1937.64
   252.1  1929.5   281.8 1922.82   311.4 1918.33   385.6 1916.91   393.2 1917.09
   408.2 1918.88   430.2 1928.66   460.2 1950.66   470.2 1953.47   490.1 1954.29
   495.1 1957.14   510.1 1971.01     555 2022.57   614.9 2061.67   639.9 2070.79
   654.8  2078.4   699.8 2112.03   724.7 2133.12   789.6 2166.74   819.6 2185.89
#Mann= 3 , 0 , 0
       0      .1       0   393.2    .045       0   408.2      .1       0
Bank Sta=393.2,408.2
XS Rating Curve= 0 ,0
Exp/Cntr=0.3,0.1

Type RM Length L Ch R = 1 ,2793.4  ,98.3,97,95
XS GIS Cut Line= 3
     1808878.607       278422.37      1808541.55      278655.846
     1808194.676      278873.316
#Sta/Elev= 30
       0 2089.46    19.8 2085.84    29.6 2081.81    69.2 2051.09   103.7 2022.03
   133.4 2001.01   192.7 1954.34   217.4 1937.17   237.1 1921.65   251.9 1912.26
   256.9 1910.12   266.8 1909.06   385.3 1909.65   394.9 1906.94   405.1 1903.14
   409.9 1905.09     440 1926.18     455 1934.94   469.9 1940.33   489.9  1941.6
   494.9 1943.31   519.9  1964.7   554.8 1999.99   639.7 2061.31   664.6 2075.57
   669.6 2076.41   734.6 2073.96   764.5 2080.12   804.4 2082.02   819.4 2081.18
#Mann= 3 , 0 , 0
       0      .1       0   394.9    .045       0   409.9      .1       0
Bank Sta=394.9,409.9
XS Rating Curve= 0 ,0
Exp/Cntr=0.3,0.1

Type RM Length L Ch R = 1 ,2696.5  ,94,95.2,96.5
XS GIS Cut Line= 2
     1808648.572      278453.355     1808369.076      278668.731
#Sta/Elev= 30
       0 1919.74     9.9 1914.62    19.9    1910    24.8 1908.06    29.8 1907.58
    64.6 1907.01   139.2    1907     164 1907.42     169 1907.12     179 1904.16
   183.9 1902.54   188.8 1902.39     194 1904.95   203.8 1911.57   223.6 1927.66
   228.6 1930.07   253.5 1937.39   263.4 1938.39   273.3 1938.32   278.3  1938.7
   283.3 1940.52   288.2 1943.35   298.2 1950.45   303.2 1954.55   313.1 1963.76
   318.1 1968.93     328 1980.13   337.9 1990.14   347.9 1999.24   352.8 2002.64
#Mann= 3 , 0 , 0
       0      .1       0     179    .045       0     194      .1       0
Bank Sta=179,194
XS Rating Curve= 0 ,0
Exp/Cntr=0.3,0.1

Type RM Length L Ch R = 1 ,2601.2  ,126.8,127.1,127.4
XS GIS Cut Line= 2
     1808678.165      278330.048     1808265.498      278617.764
#Sta/Elev= 30
       0 1964.98    29.9 1944.22    39.8 1935.38    49.8 1927.66    54.8 1924.38
    64.8 1920.36    74.7 1918.38   164.4 1905.27   239.1 1904.51   244.1 1904.11
   253.9  1901.8     259 1900.59     264 1900.55   268.9 1902.58   278.9 1907.62
   298.8 1919.56   318.8 1930.37   323.8 1931.89   333.7 1932.96   353.6 1932.95
   358.6 1933.64   373.6 1938.76   403.4 1951.72   418.4  1954.6   448.3 1965.72
   458.2 1968.02   473.2 1968.84   483.1 1970.15   493.1 1972.71   503.1 1976.54
#Mann= 3 , 0 , 0
       0      .1       0   253.9    .045       0   268.9      .1       0
Bank Sta=253.9,268.9
XS Rating Curve= 0 ,0
Exp/Cntr=0.3,0.1

Type RM Length L Ch R = 1 ,2474.2  ,209.3,204.5,199.7
XS GIS Cut Line= 2
      1808738.17      278143.773     1808073.227      278590.852
#Sta/Elev= 30
       0 2042.46    64.7 1996.76    99.5 1970.56   119.4 1959.35   144.3 1940.56
   159.3 1930.31   174.2 1921.47     209 1904.21     214 1902.58     224    1902
   313.5 1902.37   373.3 1901.48   388.1 1900.38   403.1  1898.2   413.1 1900.03
   452.9 1919.14   467.8 1923.13   492.7 1923.64   517.6 1928.39   552.4 1943.22
   567.4  1947.9   587.3 1958.32   597.2 1962.47   632.1  1970.9     642 1972.45
   696.8 1990.07   726.6  1994.8   766.4 2008.43   791.3 2015.75   801.3 2019.85
#Mann= 3 , 0 , 0
       0      .1       0   388.1    .045       0   403.1      .1       0
#XS Ineff= 2 , 0
          288.81 1902.39
Permanent Ineff=
       F       F
Bank Sta=388.1,403.1
XS Rating Curve= 0 ,0
Exp/Cntr=0.3,0.1

Type RM Length L Ch R = 1 ,2269.7  ,115.7,117.4,119
XS GIS Cut Line= 2
     1808652.676      277840.473     1808048.478      278459.931
#Sta/Elev= 30
       0 2023.35    24.9 2017.34    74.6 1993.04   134.3 1975.34     184 1956.55
   288.4 1908.37   333.2    1883   358.1 1877.33   387.9 1876.12   417.7 1877.87
   462.5 1893.04   492.2 1894.02   507.2  1895.1   517.2 1896.49     547 1906.87
   576.9 1910.35   601.8 1924.05   606.7  1927.8   611.7 1934.19   641.5 1978.48
   661.4 2005.43   681.3 2019.88   711.2 2034.48     731 2042.31   750.9  2047.6
   780.8 2057.99   815.6 2067.12   840.5 2076.59   845.4 2078.01   865.3 2077.01
#Mann= 3 , 0 , 0
       0      .1       0   492.2    .045       0   507.2      .1       0
#XS Ineff= 2 , 0
           472.1 1895.51
Permanent Ineff=
       F       F
Bank Sta=492.2,507.2
XS Rating Curve= 0 ,0
Exp/Cntr=0.3,0.1

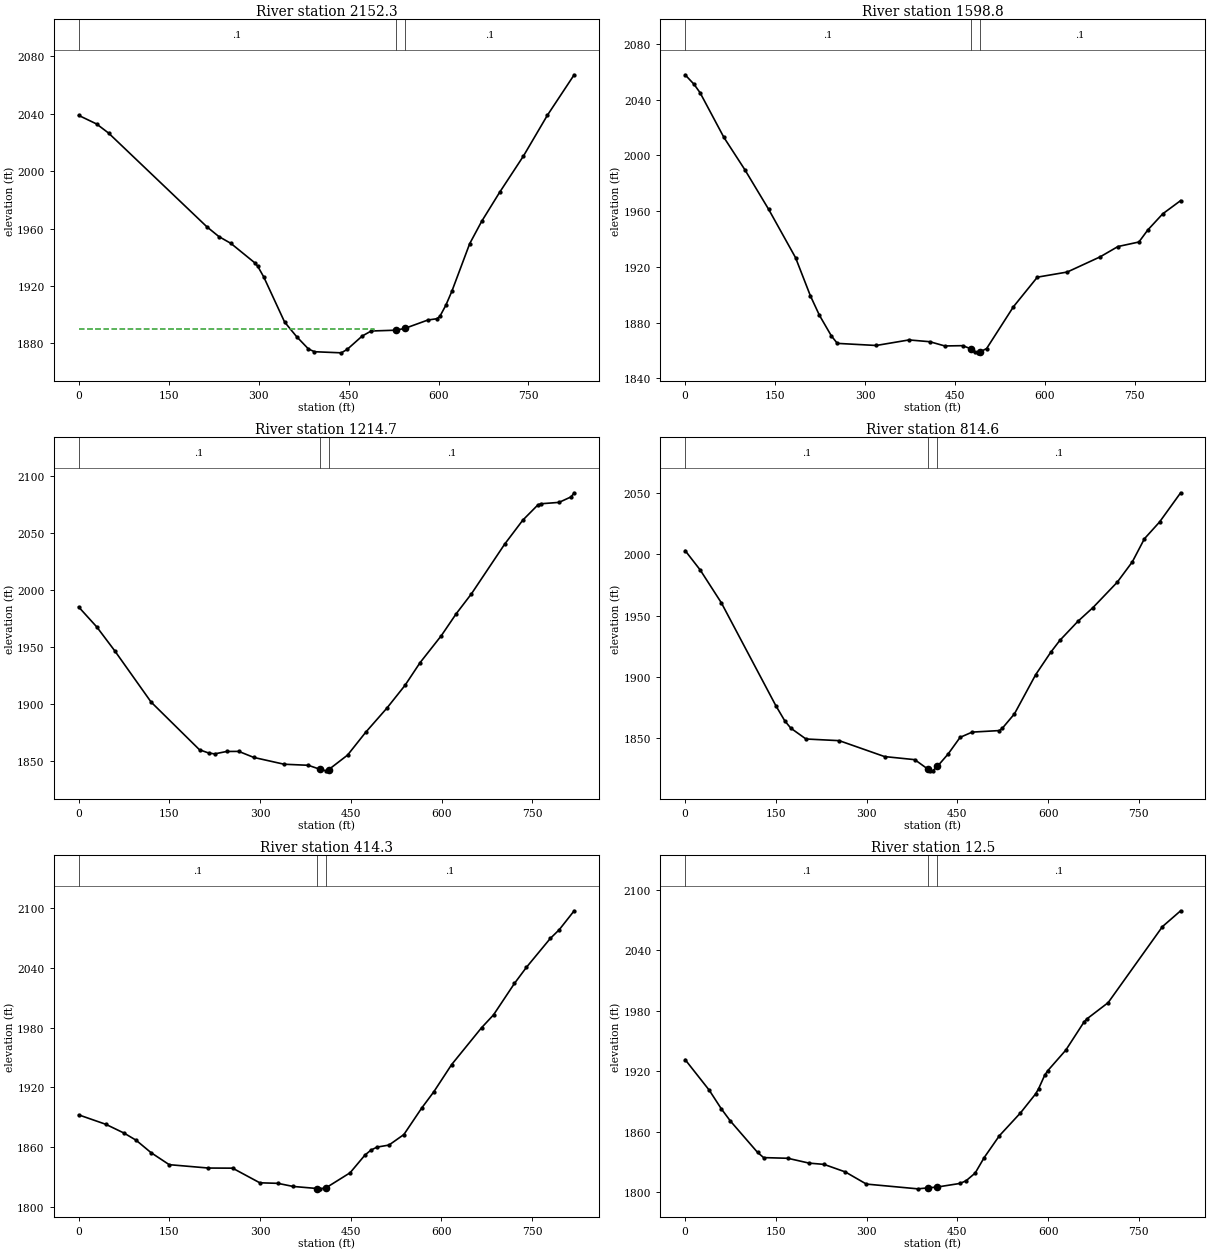
Type RM Length L Ch R = 1 ,2152.3  ,548.7,553.5,558.4
XS GIS Cut Line= 2
     1808621.887      277759.828     1808003.585      278307.877
#Sta/Elev= 30
       0 2038.86    29.9 2032.88    49.8 2026.58     214 1961.17   233.9 1954.41
   253.8  1949.7   293.7 1936.14   298.6 1933.76   308.6 1926.32   343.4 1894.89
   363.3 1884.79   383.2 1876.11   393.2 1874.21     438 1873.43     448 1875.92
   472.8 1885.14   487.8 1888.64   528.8 1889.21   543.8 1890.45   582.3 1896.29
   597.3 1897.19   602.2 1898.78   612.2 1906.55   622.2 1916.25     652 1949.48
   671.9 1964.98   701.8 1985.18   741.6 2010.52   781.4 2038.84   826.2 2067.14
#Mann= 3 , 0 , 0
       0      .1       0   528.8    .045       0   543.8      .1       0
#XS Ineff= 2 , 0
          492.47 1890.24
Permanent Ineff=
       F       F
Bank Sta=528.8,543.8
XS Rating Curve= 0 ,0
Exp/Cntr=0.3,0.1

Type RM Length L Ch R = 1 ,1598.8  ,380.3,384.1,388
XS GIS Cut Line= 2
     1808276.448      277515.579     1807546.989      277903.578
#Sta/Elev= 30
       0 2057.87    14.9 2051.06    24.9 2045.05    64.7 2012.93    99.6 1989.76
   139.4 1961.24   184.2 1926.59     209 1899.15     224 1885.26   243.9 1870.47
   253.8 1865.12   318.6 1863.61   373.3 1867.59   408.1 1866.31     433 1863.27
   462.9 1863.48   475.9  1861.3   482.8 1858.61   487.8 1858.33   490.9 1858.82
   502.7  1861.4   547.5 1891.45   587.3 1912.64   637.1 1916.31   691.8 1927.17
   721.7 1934.62   756.6 1937.86   771.5 1946.53   796.4 1958.11   826.2 1967.58
#Mann= 3 , 0 , 0
       0      .1       0   475.9    .045       0   490.9      .1       0
Bank Sta=475.9,490.9
XS Rating Curve= 0 ,0
Exp/Cntr=0.3,0.1

Type RM Length L Ch R = 1 ,1214.7  ,399.8,400.1,400.7
XS GIS Cut Line= 3
      1808084.42      277264.208     1807695.475      277392.319
     1807306.531       277520.43
#Sta/Elev= 30
       0 1985.34      30 1967.81    59.9 1946.74   119.8 1901.95   199.8 1860.14
   214.7 1857.36   224.7 1856.54   244.7 1858.67   264.7 1858.73   289.6 1853.42
   339.6 1847.48   379.5 1846.56   398.3 1843.16   409.5 1841.69   413.3 1842.77
   444.5  1855.5   474.4 1875.47   509.4 1896.62   539.3 1916.54   564.3 1936.51
   599.3 1960.07   624.2  1979.5   649.2 1996.84   704.1 2040.36   734.1 2061.42
   759.1  2074.8   764.1 2075.77     794 2076.99     814 2081.84     819  2085.4
#Mann= 3 , 0 , 0
       0      .1       0   398.3    .045       0   413.3      .1       0
Bank Sta=398.3,413.3
XS Rating Curve= 0 ,0
Exp/Cntr=0.3,0.1

Type RM Length L Ch R = 1 ,814.6   ,404.4,400.3,395
XS GIS Cut Line= 3
     1807945.562      276895.565     1807554.979      277018.982
     1807162.578      277136.034
#Sta/Elev= 30
       0 2002.91      25 1987.07    59.9 1960.39   149.9 1876.72   164.8 1864.26
   174.8 1858.31   199.8 1849.52   254.8 1848.16   329.7 1835.21   379.6  1832.7
   402.1 1824.72   404.6  1823.6   409.6  1823.8   417.1 1827.29   434.6  1837.2
   454.6 1850.86   474.5 1855.12   519.5 1856.38   524.5 1858.34   544.4 1869.98
   579.4  1901.8   604.4 1920.11   619.4 1929.76   649.3  1945.3   674.3 1956.53
   714.2 1977.07   739.2 1993.66   759.2 2012.48   784.2  2026.1   819.1 2049.92
#Mann= 3 , 0 , 0
       0      .1       0   402.1    .045       0   417.1      .1       0
Bank Sta=402.1,417.1
XS Rating Curve= 0 ,0
Exp/Cntr=0.3,0.1

Type RM Length L Ch R = 1 ,414.3   ,405.5,401.8,398.8
XS GIS Cut Line= 3
     1807737.679      276472.218     1807375.931       276663.89
     1807023.869      276874.264
#Sta/Elev= 30
       0 1892.26    44.9 1882.75    74.9 1873.96    94.9 1866.78   119.8 1854.18
   149.8 1842.11   214.7 1838.71   254.6  1838.6   299.6 1823.86   329.5 1823.32
   354.5  1820.2   394.8  1818.1   399.4 1817.78   409.8 1819.08   448.9 1833.93
   473.6 1851.83   483.5 1856.79   493.4 1859.77   513.2 1861.84   537.9 1872.44
   567.5 1899.24   587.3 1915.39   616.9 1942.91   666.3 1979.93   686.1 1992.88
   720.7 2024.51   740.5 2040.72     780 2069.82   794.8  2078.6   819.5 2097.67
#Mann= 3 , 0 , 0
       0      .1       0   394.8    .045       0   409.8      .1       0
Bank Sta=394.8,409.8
XS Rating Curve= 0 ,0
Exp/Cntr=0.3,0.1

Type RM Length L Ch R = 1 ,12.5    ,12.5,12.5,12.5
XS GIS Cut Line= 3
      1807476.99      276086.624     1807150.963      276334.407
     1806824.935       276582.19
#Sta/Elev= 30
       0 1931.61      40 1901.16    59.9 1882.74    74.9 1870.64   119.8 1839.54
   129.8  1834.4   169.8 1833.73   204.8 1828.94   229.7 1827.66   264.7 1820.22
   299.6 1808.15   384.5 1803.43     402 1804.41     417 1805.24   454.4  1808.8
   464.4 1811.44   479.4 1819.06   494.4  1834.5   519.4 1856.06   554.3 1878.72
   579.3 1897.55   584.3 1902.76   594.3 1916.04   599.3 1920.52   629.2 1940.96
   659.2 1968.74   664.2 1971.99   699.2 1988.04     789 2063.48     819 2079.13
#Mann= 3 , 0 , 0
       0      .1       0     402    .045       0     417      .1       0
Bank Sta=402,417
XS Rating Curve= 0 ,0
Exp/Cntr=0.3,0.1

Chan Stop Cuts=-1
Use User Specified Reach Order=0